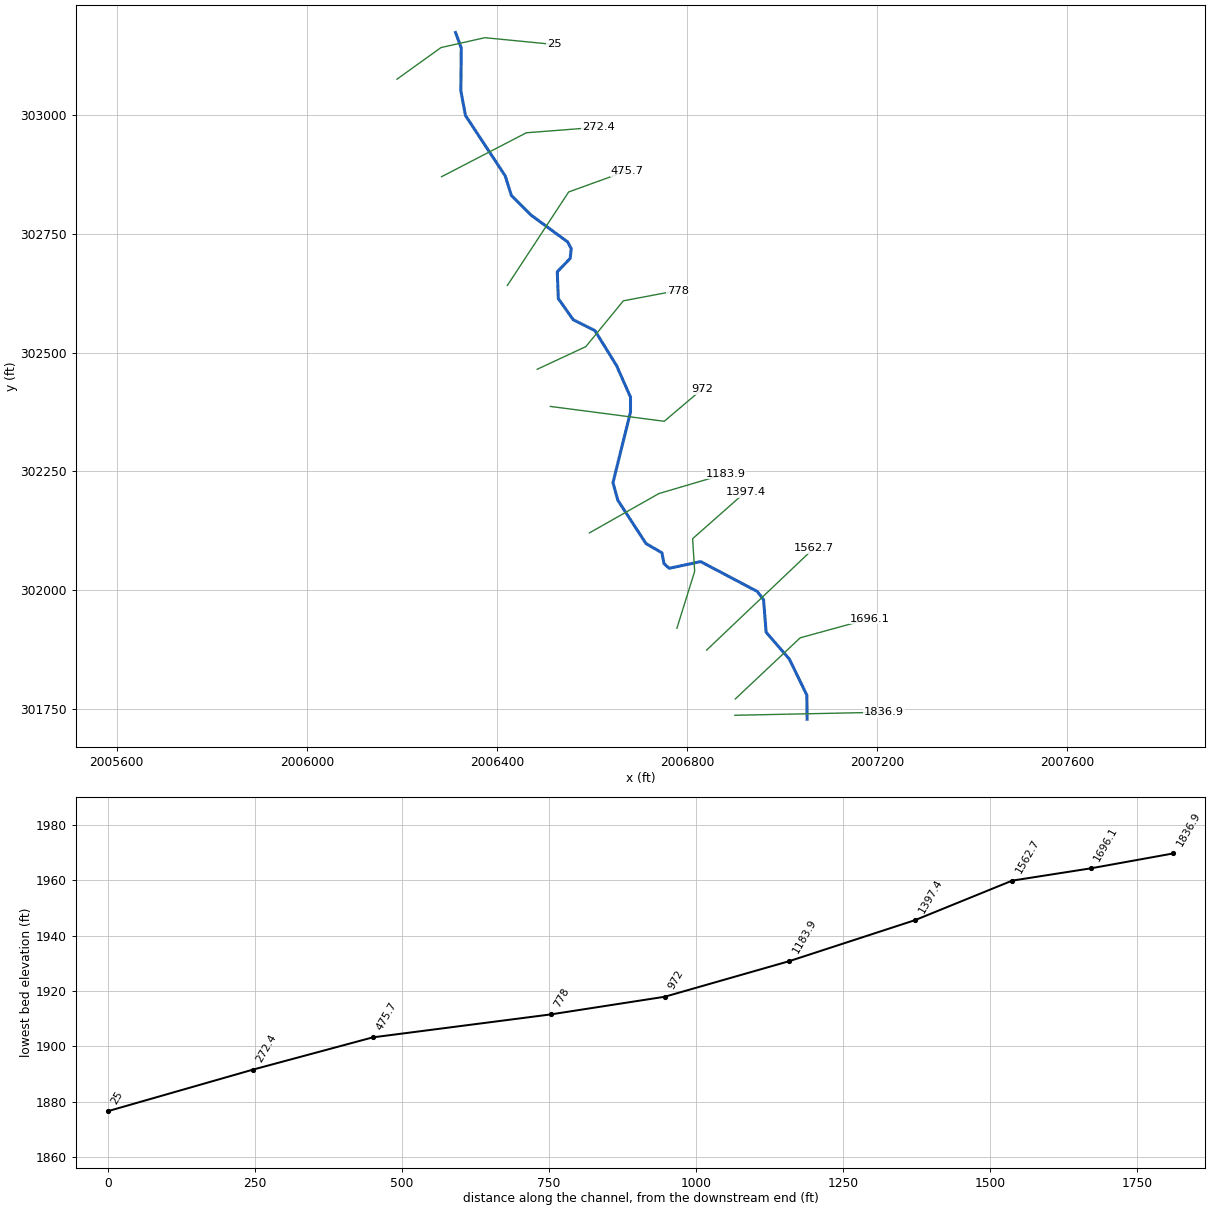
--- CLAYPOOLBR.prj (project) ---

Proj Title=CLAYPOOLBR
Current Plan=p01
Default Exp/Contr=0,0
English Units
Geom File=g01
Flow File=f01
Plan File=p01
BEGIN DESCRIPTION:
END DESCRIPTION:
DSS Export Rating Curves= 0
DSS Export Rating Curve Sorted= 0
DSS Export Volume Flow Curves= 0
DXF OffsetX= 0
DXF OffsetY= 0
DXF ScaleX= 0
DXF ScaleY= 0

--- CLAYPOOLBR.p01 (plan) ---

Plan Title=Floodplain
Program Version=4.00
Geom File=g01
Flow File=f01
K Sum by GR=0
Std Step Tol=0.01
Critical Tol=0.01
Num of Std Step Trials=20
Max Error Tol=0.3
Flow Tol Ratio=0.001
Split Flow NTrial=30
Split Flow Tol=0.02
Split Flow Ratio=0.02
Log Output Level=0
Friction Slope Method=1
Unsteady Friction Slope Method=2
Unsteady Bridges Friction Slope Method=1
Global Log Level=0
CheckData=False
Run HTab=0
Run UNet=0
Run PostProcess=0
UNET Theta=0
UNET Theta Warmup=0
UNET ZTol=0
UNET ZSATol=0
UNET MxIter=0
UNET MaxInSteps=0
UNET DtIC=0
UNET DtMin=0
UNET MaxCRTS=0
UNET WFStab=0
UNET SFStab=0
UNET WFX=0
UNET SFX=0
UNET DSS MLevel=0
UNET DZMax Abort=0
UNET Convert EG Bridges=0
UNET Use Existing IB Tables=0
UNET Froude Limit=0
UNET Froude Power=0
Write IC File=0
Echo Input=False
Echo Output=False
Write Detailed=0

--- CLAYPOOLBR.f01 (steady flow) ---

Flow Title=2010 USGS WV Regression Equation
Program Version=5.03
Number of Profiles= 1
Profile Names=P100yr
River Rch & RM=CLAYPOOLBR,Main            ,1836.9
523.5017
River Rch & RM=CLAYPOOLBR,Main            ,272.4
578.7113
Boundary for River Rch & Prof#=CLAYPOOLBR,Main            , 1
Up Type= 0
Dn Type= 3
Dn Slope=0.06055
DSS Import GetInterval= 0
DSS Import GetPeak= 0
DSS Import FillOption= 0

--- CLAYPOOLBR.g01 (geometry) ---

Geom Title=LiDAR
Program Version=4.10

River Reach=CLAYPOOLBR      ,Main
Reach XY= 30
     2007052.649      301728.405     2007052.173       301779.04
     2007015.281      301854.995     2006966.453      301911.419
     2006961.028      301979.778     2006948.007      301997.139
     2006828.649      302060.073      2006762.46      302045.967
     2006751.609      302055.733     2006747.269      302078.519
     2006713.632       302098.05     2006654.475      302189.106
     2006644.187      302226.089      2006681.08      302374.743
      2006681.08       302406.21     2006651.783      302472.399
      2006606.21      302546.184     2006560.637      302568.971
      2006529.17      302613.458        2006527.      302669.882
     2006554.127      302698.094     2006556.297       302718.71
     2006548.701      302732.816     2006471.661       302789.24
     2006430.429      302830.472     2006417.408      302871.705
     2006333.857      302998.658     2006324.092      303050.741
     2006324.959      303140.916      2006312.92      303173.441

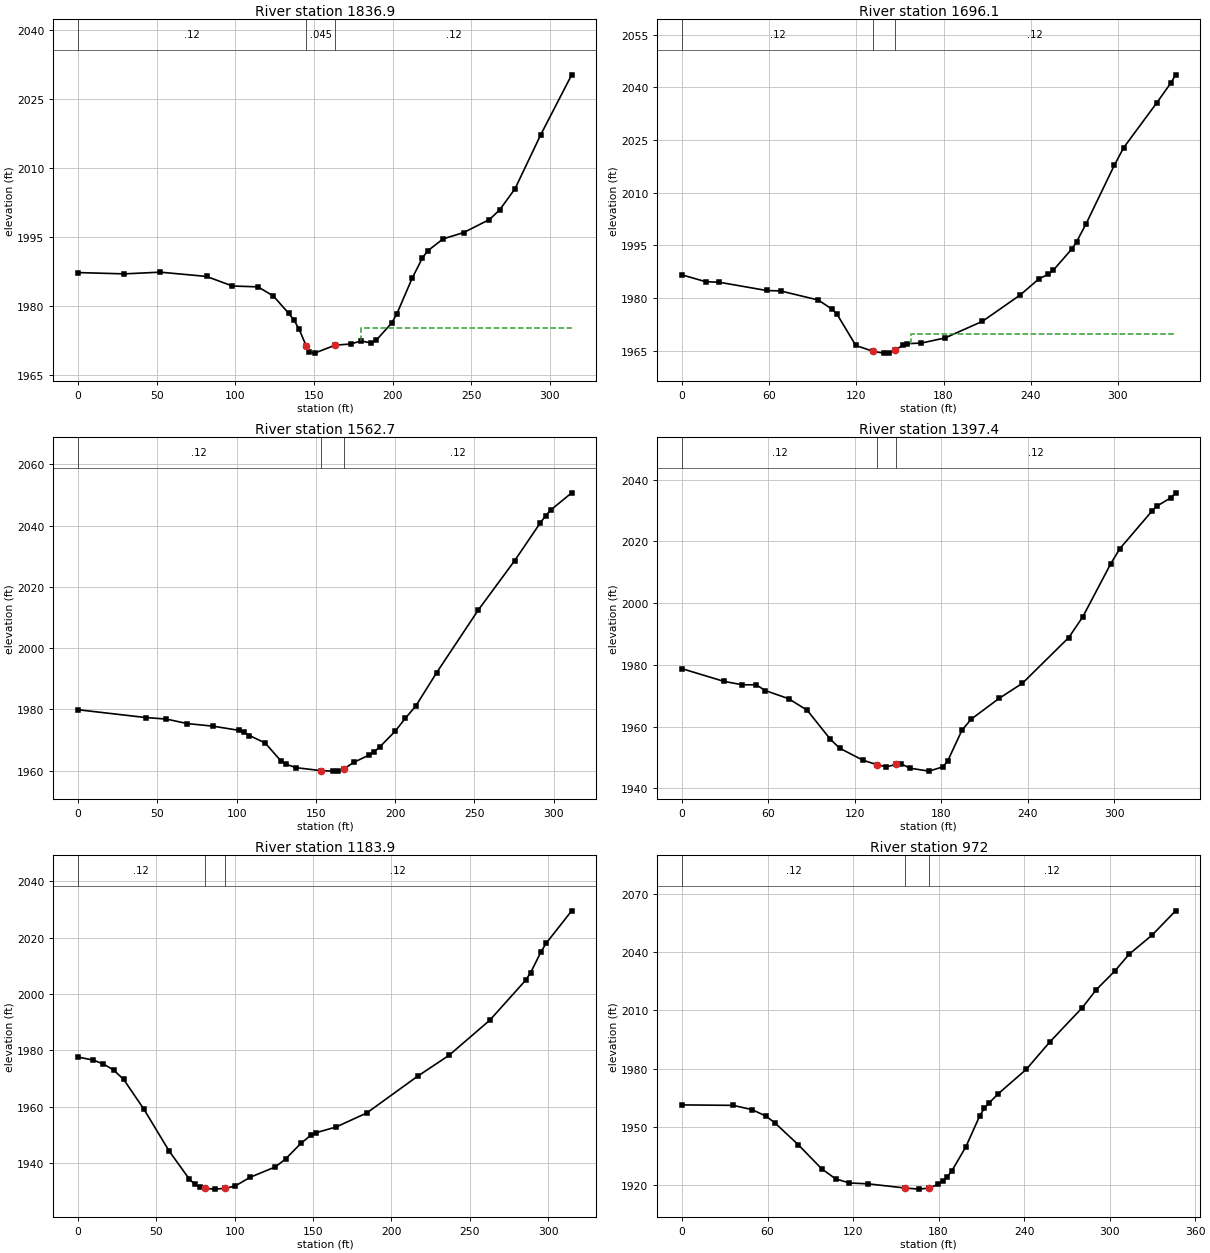
Type RM Length L Ch R = 1 ,1836.9  ,124,140.8,157.3
XS GIS Cut Line= 2
     2006900.764      301736.711     2007214.566      301743.221
#Sta/Elev= 30
       0 1987.19    29.4 1986.91    52.3 1987.28    81.7 1986.35    98.1 1984.27
   114.4 1984.08   124.2 1982.09     134 1978.29   137.3 1976.85   140.6 1974.83
  144.991971.295   147.1 1969.95   150.4 1969.66   163.5  1971.4   173.3 1971.64
   179.8  1972.3   186.4 1971.88   189.6 1972.47   199.4  1976.2   202.7  1978.2
   212.5    1986     219  1990.4   222.3 1991.91   232.1 1994.52   245.2  1995.9
   261.6 1998.74   268.1 2000.83   277.9 2005.46   294.2 2017.18   313.9 2030.23
#Mann= 3 ,-1 , 0
       0     .12       0  144.99    .045       0   163.5     .12       0
#XS Ineff= 2 , 0
                          179.88         1975.14
Permanent Ineff=
       F       F
Bank Sta=144.99,163.5
XS Rating Curve= 0 ,0
Exp/Cntr=0.3,0.1

Type RM Length L Ch R = 1 ,1696.1  ,131.5,133.4,133.3
XS GIS Cut Line= 3
     2006901.735      301771.202     2007038.143      301899.719
     2007184.949      301940.067
#Sta/Elev= 30
       0 1986.55    16.2 1984.62    25.8 1984.44    58.2  1982.1    67.9 1981.97
    93.7 1979.39   103.4 1976.77   106.6 1975.42   119.6 1966.45   131.6 1964.76
   138.9 1964.26   142.2 1964.32   146.6 1965.04   151.9  1966.5   155.1 1966.95
   164.8 1967.13     181 1968.58   206.8 1973.32   232.8 1980.83   245.7 1985.43
   252.2 1986.74   255.4 1987.81   268.4 1993.97   271.6    1996   278.1 2001.08
   297.6 2017.81     304  2022.8   326.7 2035.52   336.4 2041.18   339.7 2043.53
#Mann= 3 ,-1 , 0
       0     .12       0   131.6    .045       0   146.6     .12       0
#XS Ineff= 2 , 0
                          157.48         1969.63
Permanent Ineff=
       F       F
Bank Sta=131.6,146.6
XS Rating Curve= 0 ,0
Exp/Cntr=0.3,0.1

Type RM Length L Ch R = 1 ,1562.7  ,148.3,165.3,185.2
XS GIS Cut Line= 2
     2006841.267      301873.915     2007066.962      302088.325
#Sta/Elev= 30
       0 1979.87    42.6 1977.33    55.7 1976.82    68.8 1975.36    85.2  1974.5
   101.6 1973.13   104.9 1972.49   108.1 1971.45     118 1969.01   127.8 1963.23
   131.1 1962.08   137.6 1960.95   152.9 1960.01   160.6 1959.83   163.8 1959.93
   167.9 1960.64   173.7 1962.65   183.5 1965.08   186.8 1966.21   190.1 1967.66
   199.9  1972.8   206.4  1977.1     213 1981.11   226.1 1991.96   252.3 2012.36
   275.3 2028.52   291.6 2040.95   294.9 2043.23   298.2 2045.13   311.3 2050.69
#Mann= 3 ,-1 , 0
       0     .12       0   152.9    .045       0   167.9     .12       0
Bank Sta=152.9,167.9
XS Rating Curve= 0 ,0
Exp/Cntr=0.3,0.1

Type RM Length L Ch R = 1 ,1397.4  ,237.8,213.5,183.4
XS GIS Cut Line= 4
     2006778.767      301919.922     2006816.094      302039.714
     2006811.753       302108.29     2006922.864      302206.381
#Sta/Elev= 30
       0 1978.74      29 1974.65    41.8 1973.53    51.5 1973.52    57.9 1971.64
      74 1969.02    86.9 1965.26     103 1955.85   109.4 1952.98   125.5  1949.1
   135.3 1947.64   141.8 1946.96   148.4 1947.72   151.6    1948   158.2 1946.51
   171.3 1945.56   181.1 1946.96   184.4 1948.93   194.2  1958.8   200.6 1962.38
     220 1969.13   236.1    1974   268.3 1988.83     278 1995.51   297.3 2012.63
   303.7  2017.6   326.3 2029.95   329.5 2031.43   339.2 2034.13   342.4 2035.71
#Mann= 3 ,-1 , 0
       0     .12       0   135.3    .045       0   148.4     .12       0
Bank Sta=135.3,148.4
XS Rating Curve= 0 ,0
Exp/Cntr=0.3,0.1

Type RM Length L Ch R = 1 ,1183.9  ,226.4,211.9,196.9
XS GIS Cut Line= 3
      2006594.63      302120.482     2006740.737      302203.211
     2006881.811      302244.866
#Sta/Elev= 30
       0 1977.62     9.7 1976.52    16.1 1975.16    22.6 1973.05    29.1 1969.66
      42 1959.11    58.1 1944.29      71 1934.33    74.3 1932.58    77.5 1931.51
    80.7 1931.05    87.2 1930.78    93.6 1931.05   100.1 1931.85   109.8 1934.98
   125.9 1938.66   132.4 1941.45   142.1 1946.97   148.5 1949.86   151.8 1950.77
   164.7 1952.82   184.2 1957.78   216.9  1970.9   236.6 1978.17   262.7 1990.66
   285.6 2004.84   288.8 2007.54   295.4  2014.9   298.6 2017.88     315 2029.46
#Mann= 3 ,-1 , 0
       0     .12       0    80.7    .045       0    93.6     .12       0
Bank Sta=80.7,93.6
XS Rating Curve= 0 ,0
Exp/Cntr=0.3,0.1

Type RM Length L Ch R = 1 ,972     ,170.5,194,217
XS GIS Cut Line= 3
     2006512.448      302386.589     2006752.031      302355.339
     2006831.892      302423.047
#Sta/Elev= 30
       0 1961.33    35.9 1961.09      49 1958.92    58.8 1955.62    65.3 1951.99
    81.6 1940.79      98  1928.4   107.8  1923.2   117.5 1921.09   130.6 1920.65
   156.7 1918.48   166.5 1917.92     173 1918.47   179.6 1920.32   182.8 1921.98
   186.1 1924.25   189.4 1927.43   199.2 1939.76     209 1955.86   212.2 1959.63
   215.5 1962.37     222 1967.14   241.6 1979.69     258 1993.71   280.9 2011.48
   290.7 2020.74   303.8  2030.4   313.6 2038.92     330 2048.95   346.3 2061.35
#Mann= 3 ,-1 , 0
       0     .12       0   156.7    .045       0     173     .12       0
Bank Sta=156.7,173
XS Rating Curve= 0 ,0
Exp/Cntr=0.3,0.1

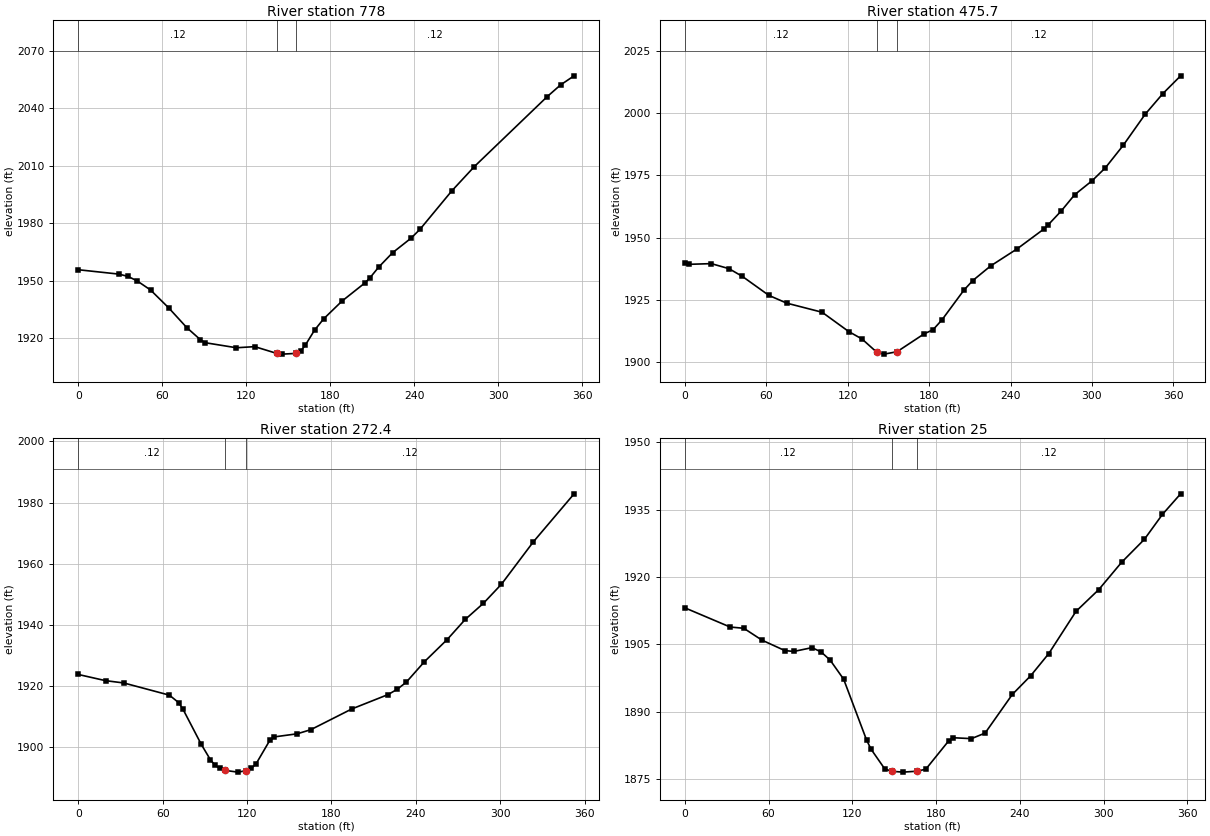
Type RM Length L Ch R = 1 ,778     ,300,302.3,304
XS GIS Cut Line= 4
      2006484.67      302464.714     2006587.101      302512.457
     2006666.094      302608.811     2006780.677      302630.513
#Sta/Elev= 30
       0 1955.63    29.1 1953.34    35.5 1952.15      42 1949.84    51.7 1945.03
    64.6 1935.73    77.5 1925.43    87.2 1919.12    90.4 1917.54     113 1914.87
   126.1 1915.45   141.9  1911.9   145.8 1911.54   155.6 1911.92   158.9 1913.15
   162.2  1916.2   168.8 1924.05   175.3 1929.95   188.4 1939.23   204.8 1948.75
   208.1 1951.15   214.6 1956.98   224.5 1964.48   237.6 1972.03   244.1 1976.72
   266.8 1996.78     283 2009.55   334.8 2045.93   344.5 2052.16   354.2 2056.93
#Mann= 3 ,-1 , 0
       0     .12       0   141.9    .045       0   155.6     .12       0
Bank Sta=141.9,155.6
XS Rating Curve= 0 ,0
Exp/Cntr=0.3,0.1

Type RM Length L Ch R = 1 ,475.7   ,214.5,203.3,190.8
XS GIS Cut Line= 3
     2006422.031      302641.224     2006550.937      302837.839
     2006673.333       302882.11
#Sta/Elev= 30
       0 1939.78     3.3 1939.33    19.6  1939.6    32.6 1937.58    42.4 1934.49
      62 1926.85    75.1 1923.74   101.2 1920.08   120.8 1912.33   130.6 1909.33
   141.4 1904.06   146.9 1903.26   156.4 1904.23   176.3 1911.38   182.9 1913.05
   189.4 1916.95   205.7 1928.99   212.2 1932.81   225.3 1938.66   244.9 1945.55
   264.4 1953.43   267.6  1955.1   277.4 1960.78   287.2 1967.25   300.2 1972.94
   309.9  1978.1     323  1987.1   339.2  1999.6   352.2 2007.87   365.3 2015.02
#Mann= 3 ,-1 , 0
       0     .12       0   141.4    .045       0   156.4     .12       0
Bank Sta=141.4,156.4
XS Rating Curve= 0 ,0
Exp/Cntr=0.3,0.1

Type RM Length L Ch R = 1 ,272.4   ,253.3,247.4,241.3
XS GIS Cut Line= 3
     2006283.576      302869.957     2006461.962      302962.405
     2006613.003      302974.124
#Sta/Elev= 30
       0 1923.65    19.4 1921.62    32.4 1920.86    64.8 1916.87    71.3 1914.45
    74.5 1912.22    87.5  1900.7      94 1895.66    97.2 1893.94   100.5 1892.86
   104.3 1892.22   113.4 1891.64   119.3  1892.1   123.1 1892.91   126.4 1894.36
   136.1 1902.01   139.4 1903.19   155.6  1904.2   165.3 1905.55   194.4 1912.34
   220.3 1917.08   226.7 1918.79   233.2 1921.14     246 1927.81   262.2 1935.09
     275 1941.67     288 1946.99   300.8 1953.24   323.4 1967.09   352.4 1982.85
#Mann= 3 ,-1 , 0
       0     .12       0   104.3    .045       0   119.3     .12       0
Bank Sta=104.3,119.3
XS Rating Curve= 0 ,0
Exp/Cntr=0.3,0.1

Type RM Length L Ch R = 1 ,25      ,19.3,25,30.6
XS GIS Cut Line= 4
     2006189.826      303075.252     2006282.274      303141.659
     2006374.722      303162.492     2006520.555      303148.169
#Sta/Elev= 30
       0 1913.16    32.5 1908.88    42.3  1908.6    55.3 1905.96    71.6 1903.65
      78 1903.44    91.1 1904.29    97.6 1903.35   104.1 1901.53   113.8 1897.27
   130.2 1883.75   133.4 1881.71   143.2 1877.33   148.21876.785   156.3  1876.6
   166.1  1876.8   172.6 1877.24     189 1883.55   192.2 1884.25   205.3 1884.05
   215.1 1885.29   234.6 1893.89   247.7 1898.03   260.7 1902.98   280.2 1912.37
   296.5 1917.21   312.8 1923.26   329.1 1928.37   342.1 1933.94   355.1 1938.51
#Mann= 3 ,-1 , 0
       0     .12       0   148.2    .045       0   166.1     .12       0
Bank Sta=148.2,166.1
XS Rating Curve= 0 ,0
Exp/Cntr=0.3,0.1

Chan Stop Cuts=-1
Use User Specified Reach Order=0
Composite Channel Slope=5